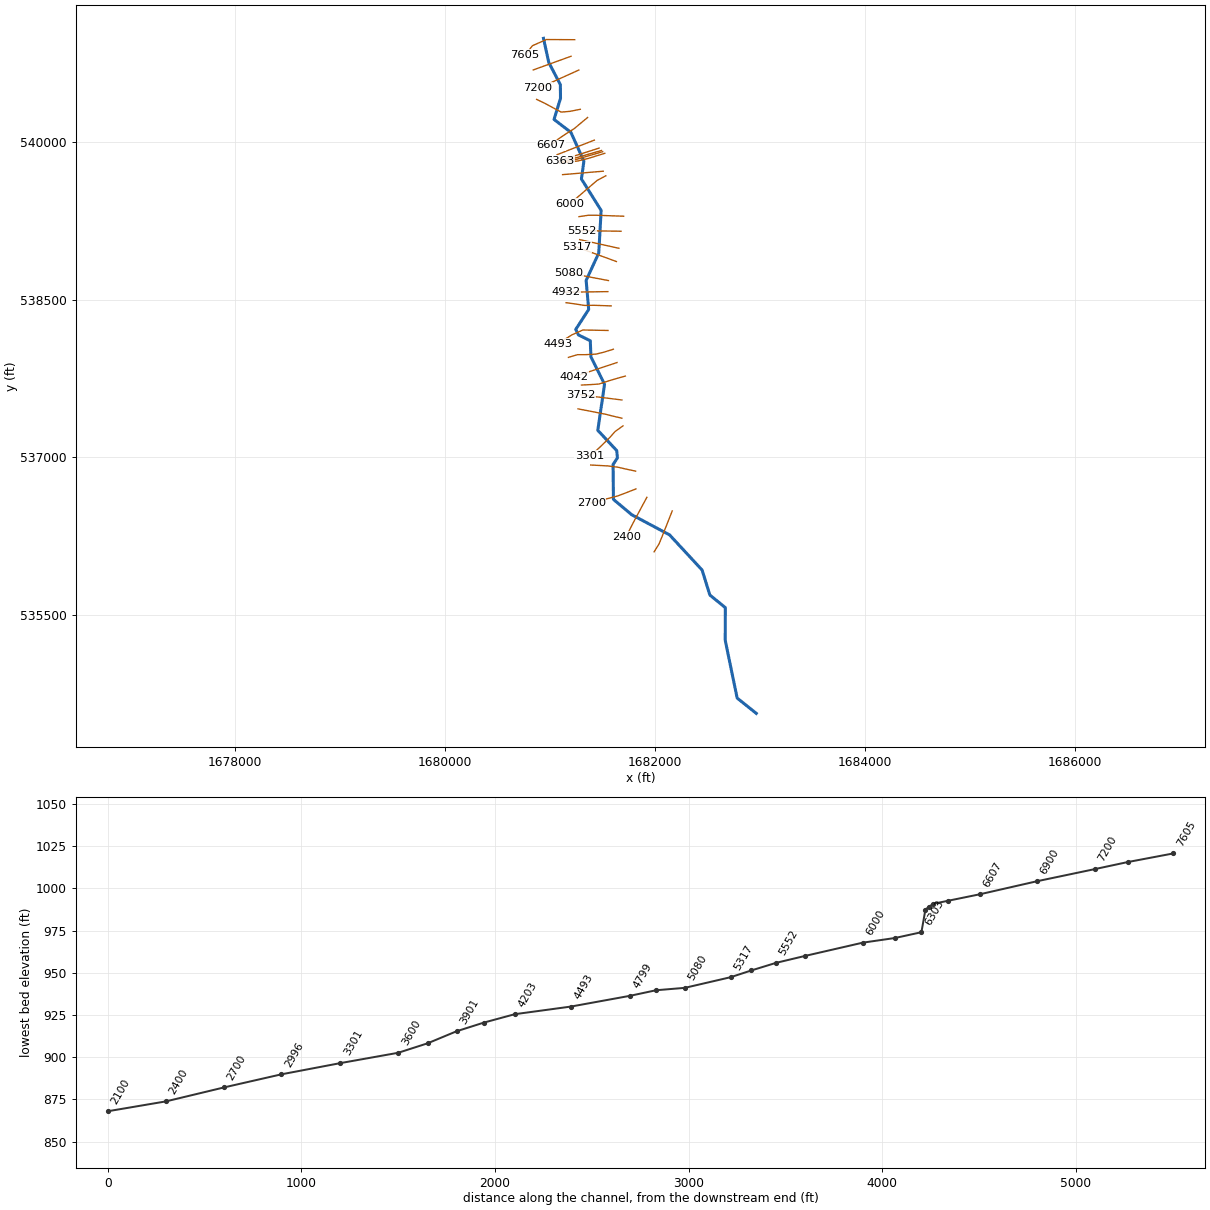
--- WhetstoneRn.prj (project) ---

Proj Title=WhetstoneRn
Current Plan=p01
Default Exp/Contr=0,0
English Units
Geom File=g01
Flow File=f01
Plan File=p01
BEGIN DESCRIPTION:
---------- MODELED AS PART OF WVEM CTP PROGRAM, 2025----------
Stream Name: Whetstone Run
Flood Zone: AFH
Marshall County, WV
HEC-RAS Version: RAS 6.6
Vertical Datum: NAVD88
Projection: NAD 1983 StatePlane West Virginia N FIPS 4701 (US Feet)
Terrain: 1-meter West Virginia FEMA R3 South Central (collected 2018-2019)
Land Use: 2024 NLCD
Hydrologic Method:
Duda et al., "Estimation of magnitude and frequency of floods for rural, unregulated streams in and near Virginia and West Virginia." September 8, 2025.
Additional Model Notes:
None
END DESCRIPTION:
DSS Export Rating Curves= 0
DSS Export Rating Curve Sorted= 0
DSS Export Volume Flow Curves= 0
DXF OffsetX= 0
DXF OffsetY= 0
DXF ScaleX= 0
DXF ScaleY= 0

--- WhetstoneRn.p01 (plan) ---

Plan Title=Floodplain
Program Version=6.60
Short Identifier=Floodplain
Geom File=g01
Flow File=f01
Subcritical Flow
K Sum by GR= 0
Std Step Tol= 0.01
Critical Tol= 0.01
Num of Std Step Trials= 20
Max Error Tol= 0.3
Flow Tol Ratio= 0.001
Split Flow NTrial= 30
Split Flow Tol= 0.02
Split Flow Ratio= 0.02
Log Output Level= 0
Friction Slope Method= 1
Unsteady Friction Slope Method= 2
Unsteady Bridges Friction Slope Method= 1
Parabolic Critical Depth
Global Vel Dist= 0 , 0 , 0
Global Log Level= 0
CheckData=False
Encroach Param=-1 ,0,0, 0
Flow Ratio Tolerance=0.1
Flow Ratio Min Ratio=0.5
Flow Ratio Max Ratio=4
Flow Ratio Max Iterations= 10
Mapping Interval=1HOUR
Computation Time Step Use Courant=        0
Computation Time Step Use Time Series=    0
Computation Time Step Count To Double=0
Computation Time Step Max Doubling=0
Computation Time Step Max Halving=0
Computation Time Step Residence Courant=0
Run HTab= 0
Run UNet= 0
Run Sediment= 0
Run PostProcess= 0
Run WQNet= 0
Run RASMapper=-1
UNET Theta= 0
UNET Theta Warmup= 0
UNET ZTol= 0
UNET ZSATol= 0
UNET MxIter= 0
UNET Max Iter WO Improvement= 0
UNET MaxInSteps= 0
UNET DtIC= 0
UNET DtMin= 0
UNET MaxCRTS= 0
UNET WFStab= 0
UNET SFStab= 0
UNET WFX= 1
UNET SFX= 1
UNET Gravity=32.17405
UNET 1D Methodology=Finite Difference
UNET DSS MLevel= 1
UNET Pardiso=0
UNET DZMax Abort= 0
UNET Use Existing IB Tables= 0
UNET Froude Reduction=False
UNET Froude Limit= 0
UNET Froude Power= 0
UNET D1 Cores= 0
UNET WindReference=Eulerian
UNET WindDragFormulation=Hsu (1988)
UNET D2 Coriolis=0
UNET D2 Cores= 0
UNET D2 Theta= 1
UNET D2 Theta Warmup= 1
UNET D2 Z Tol= 0.01
UNET D2 Volume Tol= 0.01
UNET D2 Max Iterations= 20
UNET D2 Advanced Convergence=0
UNET D2 WS Max Tol=0.15
UNET D2 WS RMS Tol=0.002
UNET D2 WS Stall Tol=1
UNET D2 Equation= 0
UNET D2 RampUpFraction=0.1
UNET D2 TimeSlices= 1
UNET D2 Turbulence Formulation=Non-Conservative (original)
UNET D2 Eddy Viscosity=0.3
UNET D2 Transverse Eddy Viscosity=0.1
UNET D2 Smagorinsky Mixing=0
UNET D2 BCVolumeCheck=0
UNET D2 Cores=0
UNET D2 SolverType=PARDISO (Direct)
UNET D2 Minimum Iterations= 3
UNET D2 Maximum Iterations= 30
UNET D2 Restart Number= 10
UNET D2 Relaxation Coeff=1.3
UNET D2 SOR Precondition Iterations= 10
UNET D2 ILUT Maximum Fill= 8
UNET D2 ILUT Tolerance=1E-08
UNET D2 Convergence Tolerance=0.00001
PS Theta= 1
PS WS Tol= 0.01
PS Volume Tol= 0.01
PS Max Iterations= 20
PS Equation= 0
PS Advance Time Step=-1
PS Target Courant=0.9
PS Time Slices= 1
PS Iterate With 2D=0
PS Project Initial WSE from DS=-1
PS Ramp Up Initial WSE from US=-1
PS Cores=0
UNET D1D2 MaxIter= 0
UNET D1D2 ZTol=0.01
UNET D1D2 QTol=0.1
UNET D1D2 MinQTol=1
Write IC File= 0
Write IC File at Fixed DateTime=0
Write IC File at Sim End=0
Echo Input=False
Echo Parameters=False
Echo Output=False
Write Detailed= 0
HDF Write Warmup=0
HDF Write Time Slices=0
HDF Flush=0
HDF Compression= 1
HDF Chunk Size= 1
HDF Spatial Parts= 1
HDF Use Max Rows=0
HDF Fixed Rows= 1
Calibration Method= 0
Calibration Iterations= 20
Calibration Max Change=0.05
Calibration Tolerance=0.2
Calibration Maximum=1.5
Calibration Minimum=0.5
Calibration Optimization Method= 1
WQ AD Non Conservative
WQ ULTIMATE=-1
WQ Max Comp Step=1HOUR
WQ Output Interval=15MIN
WQ Output Selected Increments= 0
WQ Create Restart=0
WQ Fixed Restart=0
WQ System Summary=0
WQ Write To DSS=0
Sorting and Armoring Iterations= 10
XS Update Threshold= 0.02
Bed Roughness Predictor= 0
Processes Affected by Predictor=Sediment Only
Hydraulics Update Threshold= 0.02
Energy Slope Method= 1
Volume Change Method= 1
Sediment Retention Method= 0
Sediment TS Multiplier= 1
Warm Up Method= 0
XS Weighting Method= 0
Number of US Weighted Cross Sections= 1
Number of DS Weighted Cross Sections= 1
Upstream XS Weight=0
Main XS Weight=1
Downstream XS Weight=0
Number of DS XS's Weighted with US Boundary= 1
Upstream Boundary Weight= 1
Weight of XSs Associated with US Boundary= 0
Number of US XS's Weighted with DS Boundary= 1
Downstream Boundary Weight= 0.5
Weight of XSs Associated with DS Boundary= 0.5
Percentile Method= 0
Sediment Output Level= 3
Mass or Volume Output= 0
Output Increment Type= 1
Profile and TS Output Increment= 1
Transport Output Increment 1
XS Output Flag= 0
XS Output Increment= 10
Read HDF5 Sediment Hotstart= 0
Sediment Hotstart Type= 0
Write Gradation File= 0
Read Gradation Hotstart= 0
Write HDF5 File= 1
Write Binary Output= 1
Write DSS Sediment File= 0
DSS Sediment Output Type= 1
SV Curve= 0
Specific Gage Flag= 0
Subcell Erosion Methods= 0
Subcell Deposition Methods= 0
Advection Scheme= 1
Matrix Solver= 0
Implicit Weighting Factor= 1
Maximum Outer Loop Convergence Iterations= 5
Convergence Maximum Absolute= 0.001
Convergence RMSE= 0.0001
Grain Fractions Max Abs Error= 0.001
Max Subgrid Regions= 1
Max Subgrid Length Scale= 3.402823E+38
Initial Layer Thickness= 3
Min Layer Thickness= 0.1
Max Layer Thickness= 6
Number of Layers= 5

--- WhetstoneRn.f01 (steady flow) ---

Flow Title=Flow
Program Version=6.60
Number of Profiles= 1
Profile Names=P100yr
River Rch & RM=WhetstoneRn,Main            ,7605
     756
River Rch & RM=WhetstoneRn,Main            ,4493
     842
River Rch & RM=WhetstoneRn,Main            ,3301
     937
River Rch & RM=WhetstoneRn,Main            ,898
    1410
Boundary for River Rch & Prof#=EnlowFk,Main            , 1
Up Type= 0
Dn Type= 3
Dn Slope=0.005199
DSS Import GetInterval= 0
DSS Import GetPeak= 0
DSS Import FillOption= 0

--- WhetstoneRn.g01 (geometry) ---

Geom Title=Geometry
Program Version=6.60

River Reach=WhetstoneRn     ,Main
Reach XY= 30
1680937.78464572540986.2615008061680988.42037122540756.079218388
1681098.56713255540545.6229463961681099.82500406540415.424715981
1681038.33628188540214.2522180531681198.83924173540091.201939225
1681322.53354813539817.3419226411681298.78359564539647.870148733
1681486.64673696539348.6778337211681464.00340955538942.987044066
1681343.88455531538682.4842842221681368.02131805538405.210888639
1681244.95496313 538216.175177471681270.20261605538163.280598223
1681383.31820346 538107.729200141681389.35624914 537954.76198639
1681518.97606863537693.5095561441681454.88334906537255.360169977
1681634.73174264 537062.735883311681641.61099397536992.958463803
1681600.33450171 536930.060623721681603.63666047536598.156759977
1681777.23441039536452.2338234781682137.63887331536260.395624474
1682447.72519539535925.1502319721682521.19748938535687.829184309
 1682668.6141893 535567.930145891682667.86747164535255.917646557
1682781.19926597534707.0050304831682963.41543697534561.155912727

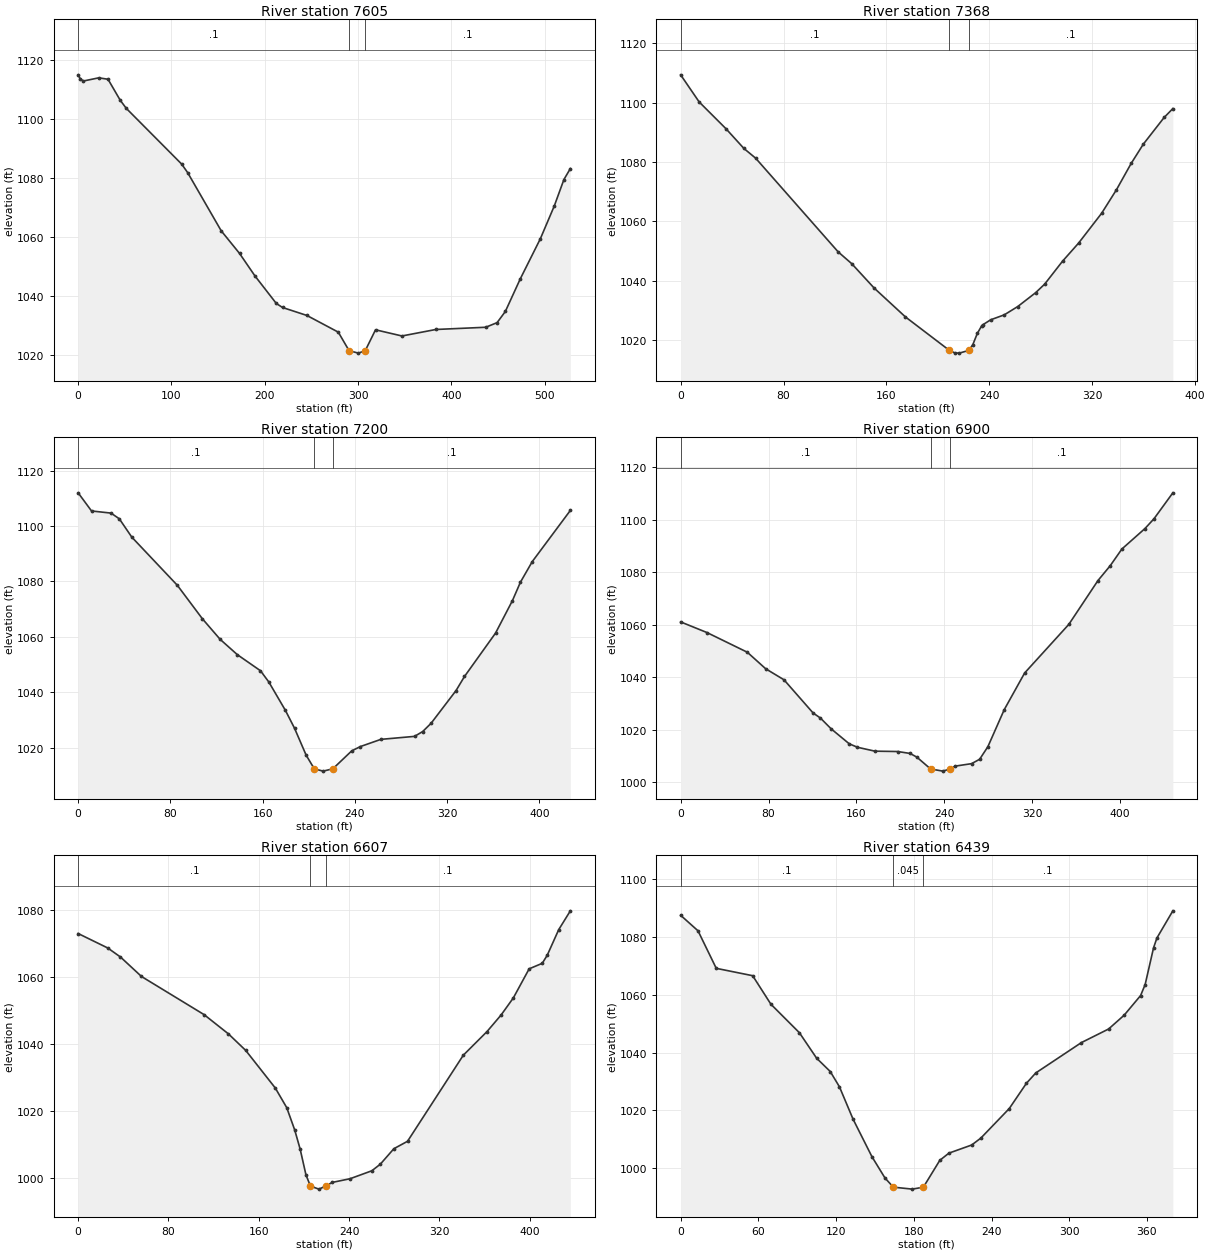
Type RM Length L Ch R = 1 ,7605    ,236.4,236.7,235
XS GIS Cut Line= 4
1681234.87761906540973.4032226371680965.21864229540974.888267994
1680833.46902798540916.3870786931680762.27059191540827.750625908
#Sta/Elev= 30
       0 1115.04     2.4 1113.62     5.7 1112.95    22.1 1114.02      32 1113.54
    45.1 1106.43    51.6 1103.68   110.9 1084.82   117.3 1081.95   153.3 1062.22
     173 1054.54   189.6 1046.88   212.4  1037.6     219 1036.25   245.2 1033.54
   278.8 1027.89  290.341021.626   300.3 1020.79  307.691021.628   318.7 1028.69
     347  1026.6   383.4  1028.8   436.8 1029.55     449 1031.12   457.8 1034.89
   473.9 1045.99   495.3  1059.5   510.2 1070.57   520.6 1079.59   527.5  1083.3
#Mann= 3 ,-1,0
       0      .1       0  290.34    .045       0  307.69      .1       0
Bank Sta=290.34,307.69
XS Rating Curve= 0 ,0
Exp/Cntr(USF)=0,0
Exp/Cntr=0.3,0.1

Type RM Length L Ch R = 1 ,7368    ,167.4,168.5,168.5
XS GIS Cut Line= 2
1681200.02058736540815.5280303781680840.13305232540685.380022423
#Sta/Elev= 30
       0 1109.33    14.4  1100.2    35.2 1091.21    49.2 1084.54    58.3 1081.28
   122.5 1049.72     133 1045.77   150.4 1037.58   174.8 1027.83  208.87  1016.6
   213.2 1015.72   216.7 1015.65  224.26  1016.6   227.2 1018.53   230.7 1022.31
   234.1 1024.86   235.1 1025.24   241.1 1026.88   251.6 1028.53   262.1 1031.33
     276 1035.99     283 1038.86   296.9 1046.58   309.4 1052.68   327.3 1062.71
   338.8 1070.61   350.3 1079.51   359.7 1085.97     376 1095.01   382.7 1097.97
#Mann= 3 ,-1,0
       0      .1       0  208.87    .045       0  224.26      .1       0
Bank Sta=208.87,224.26
XS Rating Curve= 0 ,0
Exp/Cntr(USF)=0,0
Exp/Cntr=0.3,0.1

Type RM Length L Ch R = 1 ,7200    ,306.5,300.1,290.9
XS GIS Cut Line= 6
1681274.78462793540684.7752271741681195.07579784540648.680811167
1681126.75441217540617.7428809261681035.65879384540576.491979167
1680967.59396935540544.6915178451680882.93108092540516.762111753
#Sta/Elev= 30
       0 1112.01    11.6 1105.46    28.5 1104.69    35.7 1102.63    46.5 1096.02
      86 1078.62   107.7 1066.54   123.1 1059.11     138 1053.58   158.1 1047.76
   165.3 1043.72   179.7 1033.46   187.6 1027.02   197.7 1017.27  204.751012.339
   212.4 1011.51  220.821012.339   237.2 1018.82   244.7 1020.38   262.5 1022.98
   291.7 1024.06   298.8 1025.82     306 1028.77   327.7 1040.62     335 1045.69
   361.9 1061.34   376.6 1073.11   383.5 1079.74   393.8  1087.2   426.8 1105.66
#Mann= 3 ,-1,0
       0      .1       0  204.75    .045       0  220.82      .1       0
Bank Sta=204.75,220.82
XS Rating Curve= 0 ,0
Exp/Cntr(USF)=0,0
Exp/Cntr=0.3,0.1

Type RM Length L Ch R = 1 ,6900    ,284.7,293.3,304
XS GIS Cut Line= 6
1681288.66911459540310.8931009171681189.38847326540291.121158838
1681105.81580576540284.2294403461681017.68835734540331.506248668
 1680951.6973476540367.2292743331680872.45439585540405.369946092
#Sta/Elev= 30
       0  1061.1    23.9 1057.06    60.7 1049.55    77.4 1043.27    94.1 1039.06
   120.6 1026.42   127.2 1024.52     137  1020.4   153.5 1014.69     161 1013.37
   176.9 1011.89   197.7 1011.75   208.9 1011.02   215.1  1009.6  227.571005.109
   238.7 1004.29  245.411005.106   249.9 1006.19   264.8 1007.13   272.2  1008.8
   279.7 1013.59   294.6 1027.69   313.2 1041.67   353.4 1060.16   379.9 1076.83
   391.1  1082.5   401.7 1088.85   422.7 1096.64   430.9 1100.35   448.1 1110.24
#Mann= 3 ,-1,0
       0      .1       0  227.57    .045       0  245.41      .1       0
Bank Sta=227.57,245.41
XS Rating Curve= 0 ,0
Exp/Cntr(USF)=0,0
Exp/Cntr=0.3,0.1

Type RM Length L Ch R = 1 ,6607    ,167.6,167.2,164.4
XS GIS Cut Line= 6
1681357.62206067540232.5609085111681290.21701175540176.765416428
1681232.77552558540128.5420876741681147.52864884540074.305319503
1681081.42871542540029.8674162631681010.45182326539970.241223171
#Sta/Elev= 30
       0 1073.06    26.2 1068.74    37.5 1066.03    56.1 1060.21   111.5 1048.81
   133.1 1043.04   148.4  1038.1   174.6 1026.85   184.7 1020.99   191.8 1014.29
   196.6 1008.58   201.8  1000.8  205.76997.5075   213.2  996.61  219.19997.5071
     225  998.62   240.7  999.71   260.1  1002.1   267.6 1004.07   279.6  1008.7
   291.7 1010.92   341.1 1036.67   362.1 1043.74   374.6 1048.71   385.4  1053.8
   399.4  1062.5     411 1064.15   415.4 1066.55   425.6 1074.23   435.9 1079.85
#Mann= 3 ,-1,0
       0      .1       0  205.76    .045       0  219.19      .1       0
Bank Sta=205.76,219.19
XS Rating Curve= 0 ,0
Exp/Cntr(USF)=0,0
Exp/Cntr=0.3,0.1

Type RM Length L Ch R = 1 ,6439    ,76.5,76.1,74.6
XS GIS Cut Line= 2
1681422.06033831540017.5679599261681068.21619773539879.147065552
#Sta/Elev= 30
       0 1087.59    13.4 1082.21    27.5  1069.2    55.6 1066.65    69.7 1056.76
    91.7 1046.88     105 1038.05   115.5 1033.45   122.6 1028.15   133.1 1016.95
   147.7 1003.92   157.8  996.52  164.21993.3745   178.9  992.69  187.41993.3726
   200.1 1002.68   207.1 1005.16   224.7 1007.98   231.8 1010.39   253.7 1020.61
     267  1029.4   274.2 1032.96   309.4 1043.47   330.4 1048.18   342.4 1052.96
   355.1 1059.77   358.6 1063.57   365.1 1076.31   367.7 1079.72     380 1089.13
#Mann= 3 ,-1,0
       0      .1       0  164.21    .045       0  187.41      .1       0
Bank Sta=164.21,187.41
XS Rating Curve= 0 ,0
Exp/Cntr(USF)=0,0
Exp/Cntr=0.3,0.1

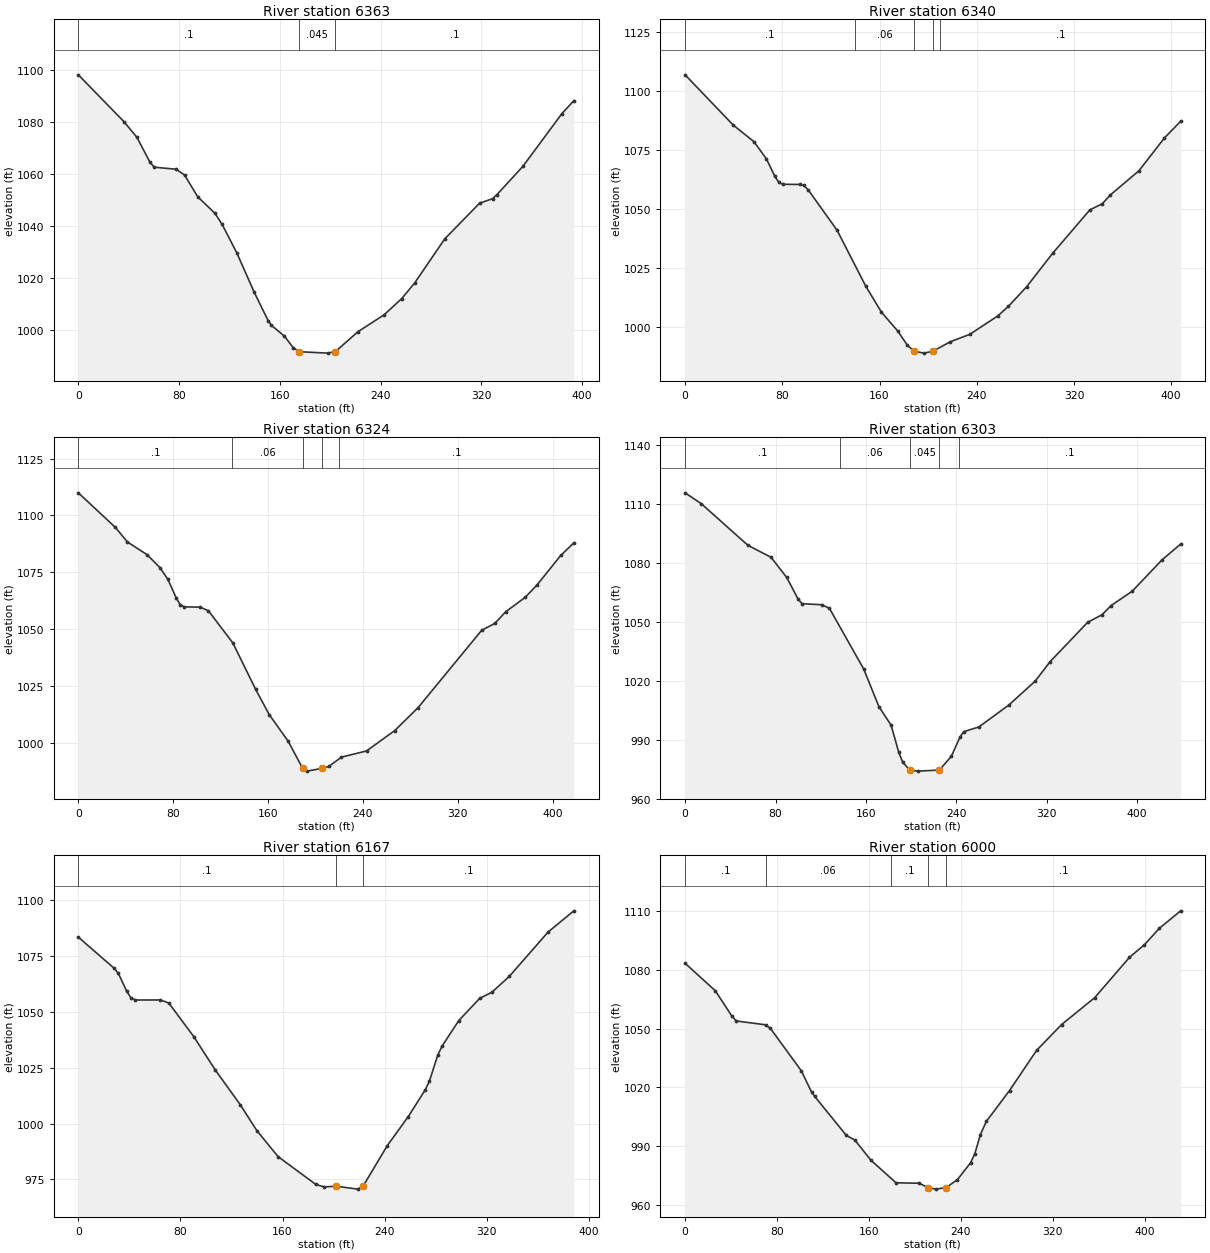
Type RM Length L Ch R = 1 ,6363    ,23.2,23.4,27.8
XS GIS Cut Line= 2
 1681467.1278533539941.3483868491681092.19973542539822.178080433
#Sta/Elev= 30
       0 1098.27    36.3 1080.17    46.6  1074.1    56.9 1064.54    60.3 1062.63
    77.6 1061.85    84.4 1059.58    94.8  1051.2   108.5 1044.84   114.2 1040.53
   125.8  1029.6   139.5 1014.54   150.7 1003.44   153.3 1001.61   163.6  997.46
   170.5  993.07  175.23991.4512     198   990.9  203.96991.4518   222.1   999.2
   242.8  1005.7   256.6 1011.88   266.9 1017.89     291 1035.04   318.5 1048.72
   328.9 1050.51   332.3 1052.03     353    1063   383.9 1083.31   393.4  1088.3
#Mann= 3 ,-1,0
       0      .1       0  175.23    .045       0  203.96      .1       0
Bank Sta=175.23,203.96
XS Rating Curve= 0 ,0
Exp/Cntr(USF)=0,0
Exp/Cntr=0.3,0.1

Type RM Length L Ch R = 1 ,6340    ,16.8,16,16.6
XS GIS Cut Line= 2
1681490.38674128539918.8019865431681098.33476707539806.681062099
#Sta/Elev= 30
       0 1106.89    39.6 1085.61    56.7 1078.56    66.9 1071.31    73.8 1063.95
    77.2 1061.29    80.6 1060.51    94.2 1060.44    97.7    1060   101.1 1058.29
     125 1041.11   148.8 1017.22   161.6 1006.33   174.9  998.39     183  992.26
  188.34989.7672   196.6  988.97  203.85989.7665   218.3   993.8   234.2  996.91
   257.2 1004.68   266.1 1008.81   281.1 1017.12   302.4 1031.23   333.1 1049.67
   343.3 1052.26     350 1056.02   373.5 1066.25   394.5 1080.17   407.8 1087.21
#Mann= 5 ,-1,0
       0      .1       0     140     .06       0  188.34    .045       0
  203.85     .06       0     210      .1       0
Bank Sta=188.34,203.85
XS Rating Curve= 0 ,0
Exp/Cntr(USF)=0,0
Exp/Cntr=0.3,0.1

Type RM Length L Ch R = 1 ,6324    ,21.9,20.8,20.7
XS GIS Cut Line= 3
1681501.85376812 539907.304171071681255.61502408539835.347004582
1681097.17722631539804.319602518
#Sta/Elev= 30
       0 1109.96    31.2 1094.79    41.4 1088.35      58 1082.74    68.8 1077.09
    75.6 1071.87    82.4 1063.91    85.8 1060.82    89.3 1059.81   102.9 1059.66
   109.8 1058.03   130.3 1043.97   149.6 1023.48     161 1012.43     177 1000.69
  189.27988.7166   192.8  987.53  205.43 988.718   211.4  989.63   221.9  993.68
   243.1   996.4   266.8 1005.33   286.5 1015.41   340.3 1049.53   351.4 1052.52
   360.4 1057.58   377.1 1064.06   387.1 1069.54     407 1082.46     418 1087.96
#Mann= 5 ,-1,0
       0      .1       0     130     .06       0  189.27    .045       0
  205.43     .06       0     220      .1       0
Bank Sta=189.27,205.43
XS Rating Curve= 0 ,0
Exp/Cntr(USF)=0,0
Exp/Cntr=0.3,0.1

Type RM Length L Ch R = 1 ,6303    ,137.1,136.3,131.6
XS GIS Cut Line= 6
1681521.70276925539892.0665107521681438.13502301539866.130210921
  1681366.505245539843.9005965891681267.92440543539819.856025249
1681188.31235993539808.6562445011681094.70362325539798.494847506
#Sta/Elev= 30
       0 1115.52    14.3 1110.02    55.5 1088.88    76.1 1082.74    89.9 1072.53
   100.2 1061.32   103.6 1059.18   120.8 1058.65   127.7 1056.86   158.1 1025.91
   171.5 1006.86   182.3  997.42     189  983.78   192.4  978.83  198.67974.6156
   205.9  974.08  225.02974.6168   235.7  981.68   243.1  991.24   246.5  994.12
     260  996.53   286.5  1007.7   309.7 1019.76     323 1029.72   356.1 1049.64
     369 1053.59     377 1058.24   395.7 1065.54   422.1 1081.49   438.5 1089.47
#Mann= 5 ,-1,0
       0      .1       0   137.5     .06       0  198.67    .045       0
  225.02     .06       0   242.5      .1       0
Bank Sta=198.67,225.02
XS Rating Curve= 0 ,0
Exp/Cntr(USF)=0,0
Exp/Cntr=0.3,0.1

Type RM Length L Ch R = 1 ,6167    ,160,166.7,171.4
XS GIS Cut Line= 2
1681506.47874999539721.5947535251681119.62443453539688.923755674
#Sta/Elev= 30
       0 1083.47    28.1  1069.5    31.4  1067.2    37.9 1059.25    41.2 1056.31
    44.7 1055.32    64.3 1055.34    70.9 1053.98    90.6 1038.79   107.1 1024.15
   126.8  1008.5     140  996.74   156.5  985.21   186.1  972.74   192.7  971.66
  201.96  971.96     219  970.66  223.05971.9604   242.1  990.18   258.5 1003.14
   271.7 1015.05     275 1018.96   281.6 1030.68   284.9 1034.64     298 1046.08
   314.5 1056.11     324 1058.78   337.6 1065.88     368 1085.74   388.2 1095.24
#Mann= 3 ,-1,0
       0      .1       0  201.96    .045       0  223.05      .1       0
Bank Sta=201.96,223.05
XS Rating Curve= 0 ,0
Exp/Cntr(USF)=0,0
Exp/Cntr=0.3,0.1

Type RM Length L Ch R = 1 ,6000    ,305,300,292.2
XS GIS Cut Line= 6
1681531.05248809539677.6663490091681448.17010793539633.864927426
1681391.27127159539585.0015080871681315.42791934539519.826441586
 1681258.5113665539470.9859880951681192.11812659539413.994632259
#Sta/Elev= 30
       0 1083.39    26.3 1069.33    40.7 1056.38    44.6 1053.88      70 1051.93
    74.3 1050.05   101.2 1028.34     110 1017.56   112.8 1015.29   140.2  995.42
   147.7  992.99   161.7  982.66   183.5  971.14   203.6   970.9   211.5 968.687
   218.1  967.89  227.24968.6863     237  972.78   248.4  981.37   252.1  985.99
     257   995.8   262.1  1002.5   282.3 1018.31   305.9 1038.88   327.6 1052.04
   356.5 1065.85   386.7 1086.43   399.7 1092.88   412.7 1101.28   431.2 1110.21
#Mann= 5 ,-1,0
       0      .1       0      70     .06       0  178.75      .1       0
   211.5    .045       0  227.24      .1       0
Bank Sta=211.5,227.24
XS Rating Curve= 0 ,0
Exp/Cntr(USF)=0,0
Exp/Cntr=0.3,0.1

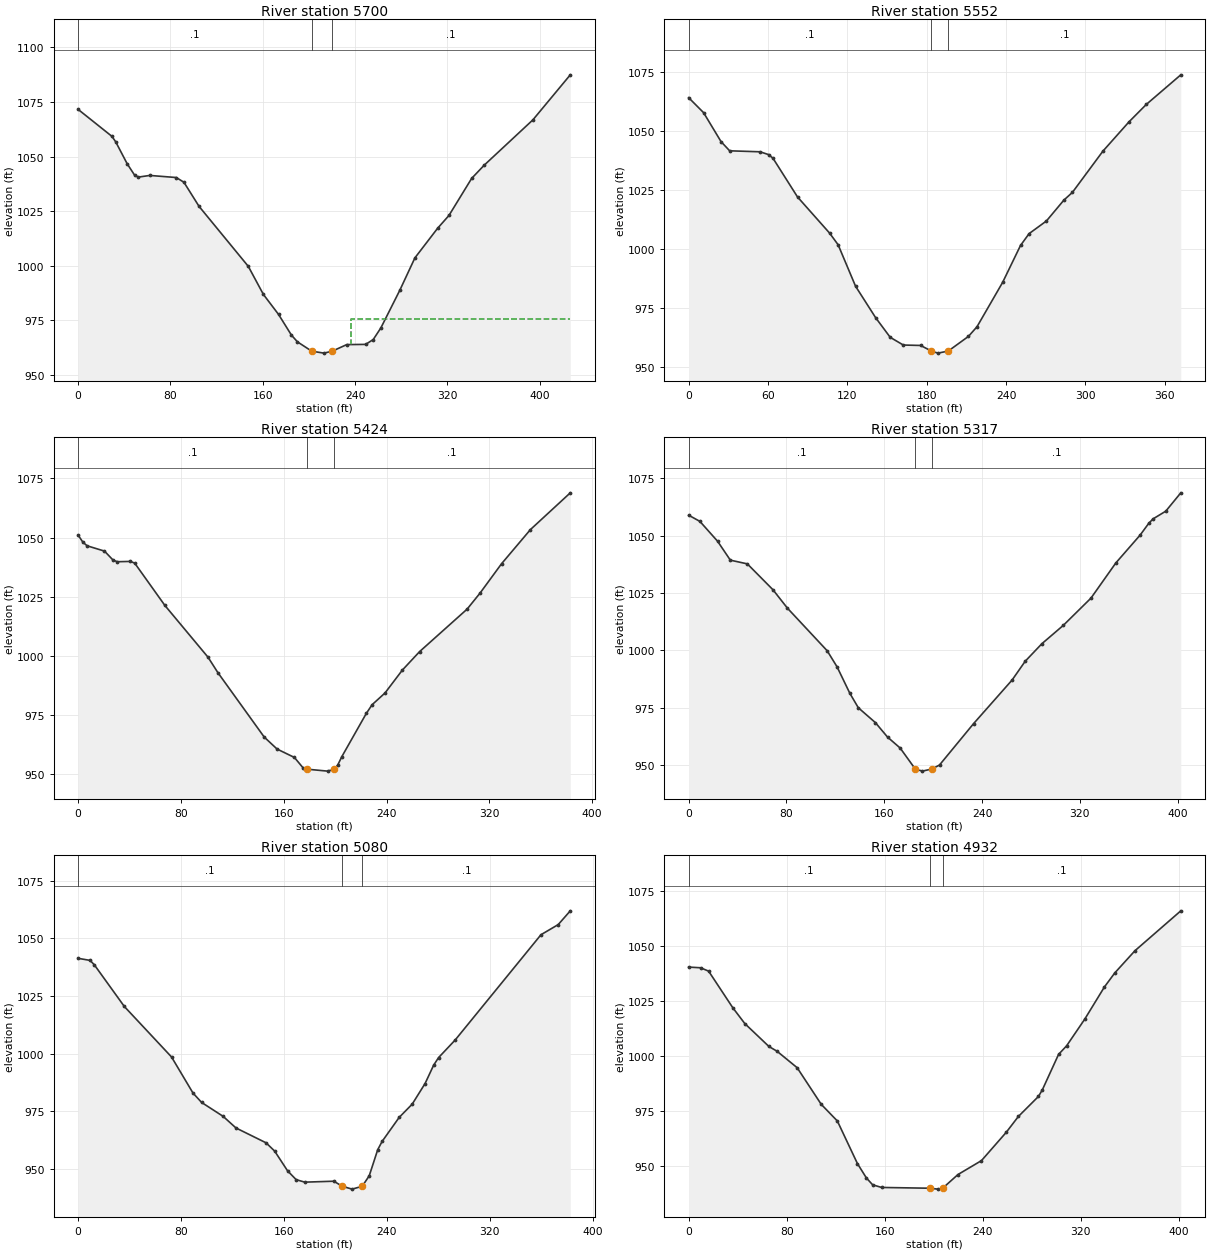
Type RM Length L Ch R = 1 ,5700    ,147.8,148.2,148.2
XS GIS Cut Line= 6
  1681701.339221   539293.0608191681613.89484209539296.183516175
1681538.94256417539298.8603480911681439.00641234539302.429238588
 1681363.9521005539302.245840013 1681275.9247175539289.041142002
#Sta/Elev= 30
       0 1071.57    29.3 1059.23    32.6 1056.69    42.5 1046.68      49 1041.42
    52.3 1040.59    62.1 1041.34    85.1 1040.38    91.7 1038.21   104.8 1027.18
   147.5   999.7   160.6  986.84   173.7  977.71   184.9  968.21   190.1  965.14
  202.49960.8726   213.1  959.98  220.21960.8707   232.8  963.88   249.2  963.98
   255.8  966.21   262.4  971.53   278.8  988.74   291.9 1003.59   311.6 1017.16
   321.4    1023   341.1 1039.99     352 1046.05   394.2  1066.8   426.6 1087.41
#Mann= 3 ,-1,0
       0      .1       0  202.49    .045       0  220.21      .1       0
#XS Ineff= 2 , 0
                          236.45          975.46
Permanent Ineff=
       F       F
Bank Sta=202.49,220.21
XS Rating Curve= 0 ,0
Exp/Cntr(USF)=0,0
Exp/Cntr=0.3,0.1

Type RM Length L Ch R = 1 ,5552    ,128.8,127.8,125.7
XS GIS Cut Line= 2
1681676.84645343539150.0172961731681304.76008902539155.792472561
#Sta/Elev= 30
       0 1064.15    11.3 1057.79    24.5 1045.52      31 1041.64      54 1041.22
    60.5 1040.02    63.8 1038.45    82.3 1022.09   106.5 1006.81     113 1001.84
   126.2  984.25   141.4  970.91   152.4  962.61   162.3  959.35   175.4  959.17
  183.57956.7894   188.5  955.92  196.24956.7896   211.5  962.99     218  967.09
   237.4  985.91   250.9 1001.53   257.4 1006.55   270.5 1011.91   283.7 1020.75
   290.2 1024.06   313.2 1041.49   332.9 1053.89     346 1061.28   372.1 1073.83
#Mann= 3 ,-1,0
       0      .1       0  183.57    .045       0  196.24      .1       0
Bank Sta=183.57,196.24
XS Rating Curve= 0 ,0
Exp/Cntr(USF)=0,0
Exp/Cntr=0.3,0.1

Type RM Length L Ch R = 1 ,5424    ,106.1,107.1,104.6
XS GIS Cut Line= 2
1681655.96695424538987.9859355241681281.95553102 539070.48845535
#Sta/Elev= 30
       0 1050.99     3.7 1048.04       7 1046.51    20.5 1044.27    27.2 1040.47
    30.5 1039.79    40.6 1039.92      44 1039.21    67.5 1021.34   101.1  999.47
   108.7  993.01   144.8  965.79   154.8  960.73   168.3  957.18     175  952.81
  178.27952.2233   194.1  951.41  199.23952.2215   201.9  953.86   205.2  957.52
   224.3  975.81   228.8  979.46   238.8  984.39   252.3  994.05   265.7 1001.84
   302.7 1019.79   312.7  1026.5   329.5 1038.94     352 1053.37     383 1068.87
#Mann= 3 ,-1,0
       0      .1       0  178.27    .045       0  199.23      .1       0
Bank Sta=178.27,199.23
XS Rating Curve= 0 ,0
Exp/Cntr(USF)=0,0
Exp/Cntr=0.3,0.1

Type RM Length L Ch R = 1 ,5317    ,235.5,236.7,237.3
XS GIS Cut Line= 2
1681631.92043241538861.9690616971681253.62675582538999.880197463
#Sta/Elev= 30
       0 1058.87     9.2 1056.17    23.6 1047.57    34.1 1039.29      48 1037.67
      69 1026.38    80.8 1018.38   113.3  999.84   121.4  992.83   131.9  981.26
   138.8     975   152.8  968.52   162.7  962.23     173  957.48  185.35948.3487
   191.2  947.41  199.06948.3479   205.2  950.07   233.1  968.11   264.6  987.09
   275.3  995.26     289 1002.92   306.5  1010.9   329.1 1022.75   349.5 1038.11
   369.3 1050.19   376.3 1055.27   379.8 1057.23   390.3 1060.62   402.6 1068.61
#Mann= 3 ,-1,0
       0      .1       0  185.35    .045       0  199.06      .1       0
Bank Sta=185.35,199.06
XS Rating Curve= 0 ,0
Exp/Cntr(USF)=0,0
Exp/Cntr=0.3,0.1

Type RM Length L Ch R = 1 ,5080    ,147.4,148.3,150.5
XS GIS Cut Line= 2
1681556.44569069538680.6421561911681180.58569923538752.059454763
#Sta/Elev= 30
       0 1041.33     9.2 1040.44    12.5 1038.58    35.9 1020.42    72.6  998.49
    89.3  982.81      96  978.74   112.7  972.71   122.7  967.66   146.1  961.21
   152.8   957.6   162.8  949.05   169.5  945.21   176.2  944.13   198.8  944.54
  205.26942.3436     213   941.1  220.87942.3453   226.3  946.91   232.9  958.24
   236.3  961.81   249.6  972.27   259.7  978.01   269.7  986.96   276.4  994.96
   280.2  998.22   293.1 1005.86   359.8 1051.58   373.2 1055.98   382.6 1061.96
#Mann= 3 ,-1,0
       0      .1       0  205.26    .045       0  220.87      .1       0
Bank Sta=205.26,220.87
XS Rating Curve= 0 ,0
Exp/Cntr(USF)=0,0
Exp/Cntr=0.3,0.1

Type RM Length L Ch R = 1 ,4932    ,132.1,133,131
XS GIS Cut Line= 2
1681550.59323008538575.4496238861681149.08096693538569.949455898
#Sta/Elev= 30
       0 1040.46     9.7 1040.15    16.3 1038.61      36 1022.01    45.8 1014.83
    65.5 1004.42    72.1 1002.27    88.5   994.8   108.2  978.14   121.3  970.62
   137.7  951.27     145  944.76   150.1  941.65   157.4  940.45   196.7   940.1
   203.3  939.69  207.22  940.11   219.7  946.31   238.9  952.64   259.1  965.48
     269  972.67   285.4  981.77   288.6  984.82   301.8 1000.86   308.3  1004.7
   323.1  1016.8   339.2 1031.45   347.7 1037.85   364.1 1047.89   401.5 1065.99
#Mann= 3 ,-1,0
       0      .1       0   196.7    .045       0  207.22      .1       0
Bank Sta=196.7,207.22
XS Rating Curve= 0 ,0
Exp/Cntr(USF)=0,0
Exp/Cntr=0.3,0.1

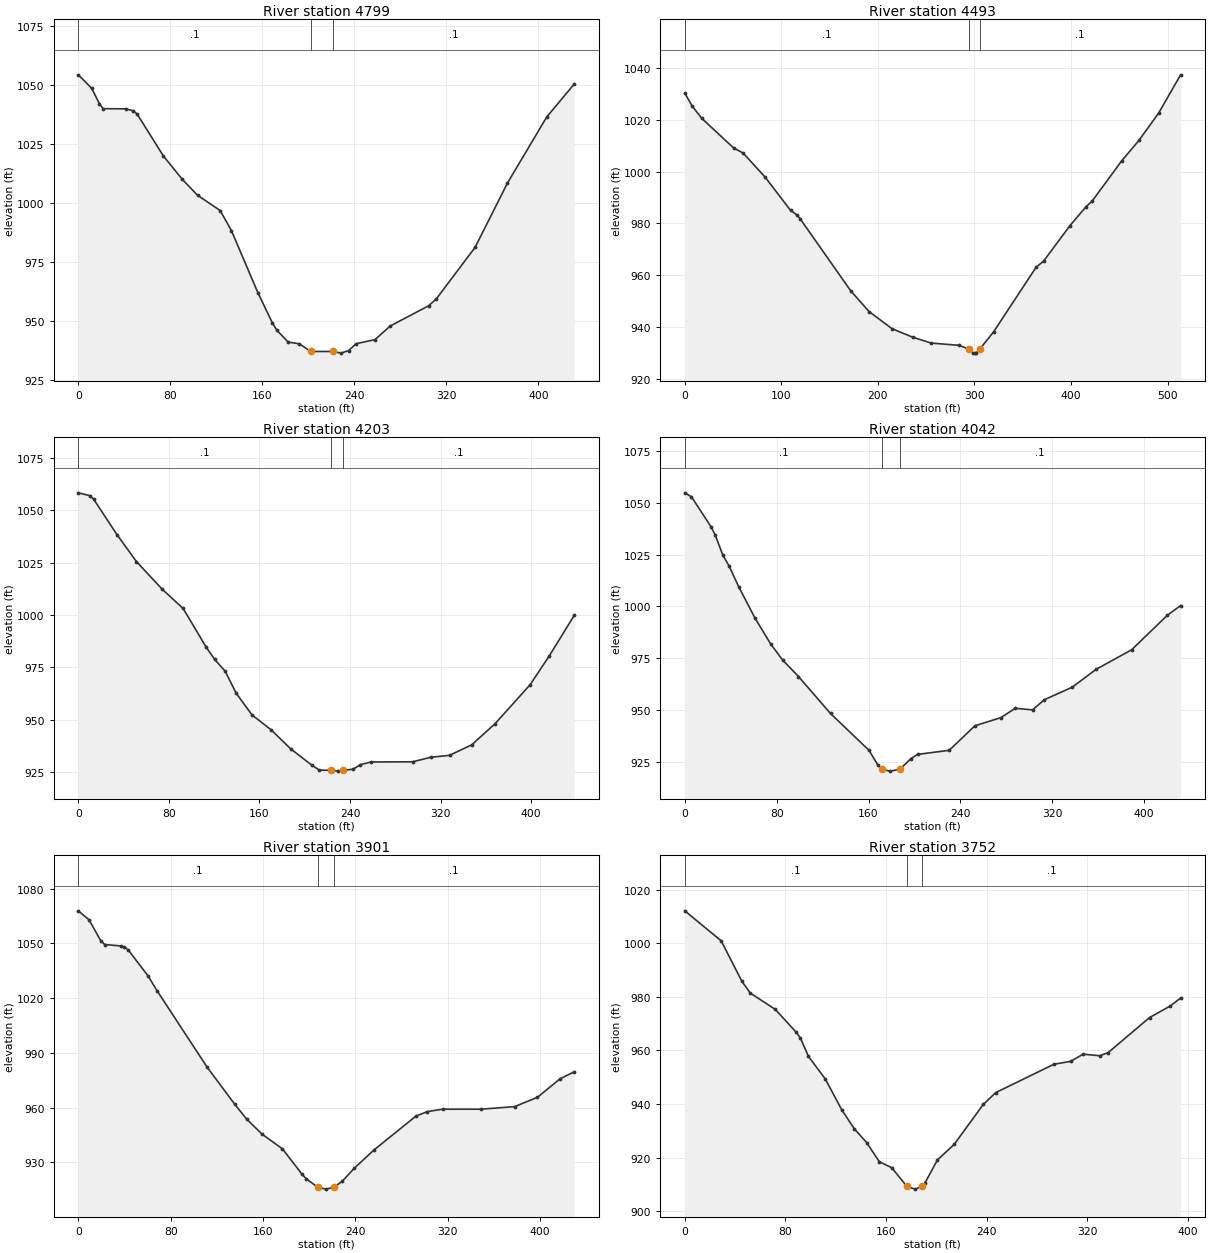
Type RM Length L Ch R = 1 ,4799    ,301.6,306.3,301.4
XS GIS Cut Line= 5
1681582.02997041538439.5246646221681417.11890822538445.421140174
1681328.96894812538443.9698714241681246.12425217538457.416492924
 1681153.0312625538469.832806677
#Sta/Elev= 30
       0 1054.34    11.7 1048.57    18.2 1042.19    21.5    1040    41.2 1039.93
    47.8 1039.09    51.1 1037.72      74 1019.91    90.5 1009.99   103.6 1003.32
   123.3  996.84   133.1  988.31   156.1     962   168.6   949.3   172.5  946.16
   182.4  941.12   192.2  940.36  202.07  937.11   221.7  937.11   228.3  936.42
   234.9  937.49   241.4   940.4   257.9  942.16   271.2  947.93   304.4  956.46
   311.1  959.36   344.9  981.24     373 1008.47   407.2 1036.51     431 1050.41
#Mann= 3 ,-1,0
       0      .1       0  202.07    .045       0   221.7      .1       0
Bank Sta=202.07,221.7
XS Rating Curve= 0 ,0
Exp/Cntr(USF)=0,0
Exp/Cntr=0.3,0.1

Type RM Length L Ch R = 1 ,4493    ,288.5,290.1,284.1
XS GIS Cut Line= 5
1681551.98089039538205.7199734981681312.58901426538210.221121177
1681210.62760401 538164.967602761681146.88626167538125.439138502
1681072.05078143538080.064557344
#Sta/Elev= 30
       0 1030.24     7.9 1025.11    17.7 1020.49    50.5 1009.12    60.4 1007.16
    83.3  997.82   109.6  985.01   116.1  983.32   119.4  981.85   171.9  954.01
   190.8  946.05   214.6  939.45   235.9  936.17   255.3  933.89   284.1  933.03
  294.09931.5696   298.4  930.09   300.2  930.02     302  930.08  305.48931.5678
   319.9  938.28   363.9  963.16   371.6  965.49   398.8  979.13   415.5  986.44
   421.8  988.59   452.5 1004.16   470.4 1012.05   490.9 1022.66   513.5  1037.3
#Mann= 3 ,-1,0
       0      .1       0  294.09    .045       0  305.48      .1       0
Bank Sta=294.09,305.48
XS Rating Curve= 0 ,0
Exp/Cntr(USF)=0,0
Exp/Cntr=0.3,0.1

Type RM Length L Ch R = 1 ,4203    ,162.3,160.2,163.2
XS GIS Cut Line= 6
1681602.97196367538027.150949255 1681513.7510135537999.371149167
  1681436.788569537980.4774861781681336.13588317537975.384320512
1681261.13570508537975.3843205121681175.41081092537949.559569001
#Sta/Elev= 30
       0 1058.38    10.1 1057.04    13.5 1055.38    34.1 1038.45    51.3 1025.59
    74.1 1012.35    92.6 1003.16   112.8  984.81   120.5   978.8   129.7   973.2
   139.5  962.67   153.4  952.34   170.3  945.23   187.6  936.14   206.5  928.24
     213  925.97   222.9   925.9   229.5   925.5  233.56   925.9   242.6  926.38
   249.2  928.58   258.5  929.87   295.3  929.95   311.5  932.13   327.9  933.04
   347.6   938.1   368.2  948.19     399  966.69   416.1  980.58     438  999.81
#Mann= 3 ,-1,0
       0      .1       0   222.9    .045       0  233.56      .1       0
Bank Sta=222.9,233.56
XS Rating Curve= 0 ,0
Exp/Cntr(USF)=0,0
Exp/Cntr=0.3,0.1

Type RM Length L Ch R = 1 ,4042    ,141,141,140.9
XS GIS Cut Line= 2
1681638.17057157537900.5405105351681228.13304803 537765.23637802
#Sta/Elev= 30
       0 1054.77     5.8 1052.86      23 1038.28    26.5 1034.41    33.2 1024.64
    38.4 1019.65    47.2 1009.18      61  994.48    74.8  981.84    85.2  974.11
      99  966.16   126.9  948.32   160.5   930.5   168.1  923.44  171.59921.3446
   178.5  920.51  187.18921.3433   196.9  926.54   202.7  928.58   230.3  930.56
   252.6  942.38   275.2  946.31   287.8  950.81   302.9  950.07   313.2  954.99
   337.4  960.99   358.1  969.59   389.1  979.04   420.3  995.72   431.8 1000.39
#Mann= 3 ,-1,0
       0      .1       0  171.59    .045       0  187.18      .1       0
Bank Sta=171.59,187.18
XS Rating Curve= 0 ,0
Exp/Cntr(USF)=0,0
Exp/Cntr=0.3,0.1

Type RM Length L Ch R = 1 ,3901    ,150.9,149.4,144.9
XS GIS Cut Line= 6
1681717.16235209537771.5382715021681632.68909584537748.235824674
1681560.78536826537726.623006999  1681465.646779537695.719853595
   1681389.55638537690.5935515021681299.01751909537686.229058921
#Sta/Elev= 30
       0 1067.84     9.3 1062.91    19.5 1051.38    22.9 1049.36    36.6 1048.62
      40 1048.03    43.4 1046.32    60.4 1032.18    68.1 1024.18   111.6  982.17
   135.6  961.81   145.8  953.77   159.5  945.32   176.8  937.48     194  923.39
   197.5  921.06  207.42916.3965   214.7  915.37  221.32916.3987   228.5  919.56
   238.9  926.71   256.1  936.79   292.6  955.42   302.5  957.84   315.6  959.16
   348.5  959.16     378  960.56   397.8  965.68   417.4  975.82   429.6  979.63
#Mann= 3 ,-1,0
       0      .1       0  207.42    .045       0  221.32      .1       0
Bank Sta=207.42,221.32
XS Rating Curve= 0 ,0
Exp/Cntr(USF)=0,0
Exp/Cntr=0.3,0.1

Type RM Length L Ch R = 1 ,3752    ,152.1,151.9,151.3
XS GIS Cut Line= 2
1681684.37198267537544.129624887 1681293.3100387537592.806111584
#Sta/Elev= 30
       0 1012.09    28.9  1000.9    45.4  985.78    52.1  981.39    71.9  975.32
    88.4  966.86    91.9  964.65    98.3  957.76   111.6   949.4   124.8   937.8
   134.7  930.78   144.6  925.57   154.6  918.49   164.5  916.21  176.61909.2224
     183  908.24   188.6909.2227   190.9  910.54   200.8  919.14   214.1  924.92
   237.2  939.82   247.1  944.25   293.4  954.84   306.6  955.92   316.6  958.59
   329.8  958.02   336.4  959.14   369.4  972.27   385.9  976.58   394.1  979.58
#Mann= 3 ,-1,0
       0      .1       0  176.61    .045       0   188.6      .1       0
Bank Sta=176.61,188.6
XS Rating Curve= 0 ,0
Exp/Cntr(USF)=0,0
Exp/Cntr=0.3,0.1

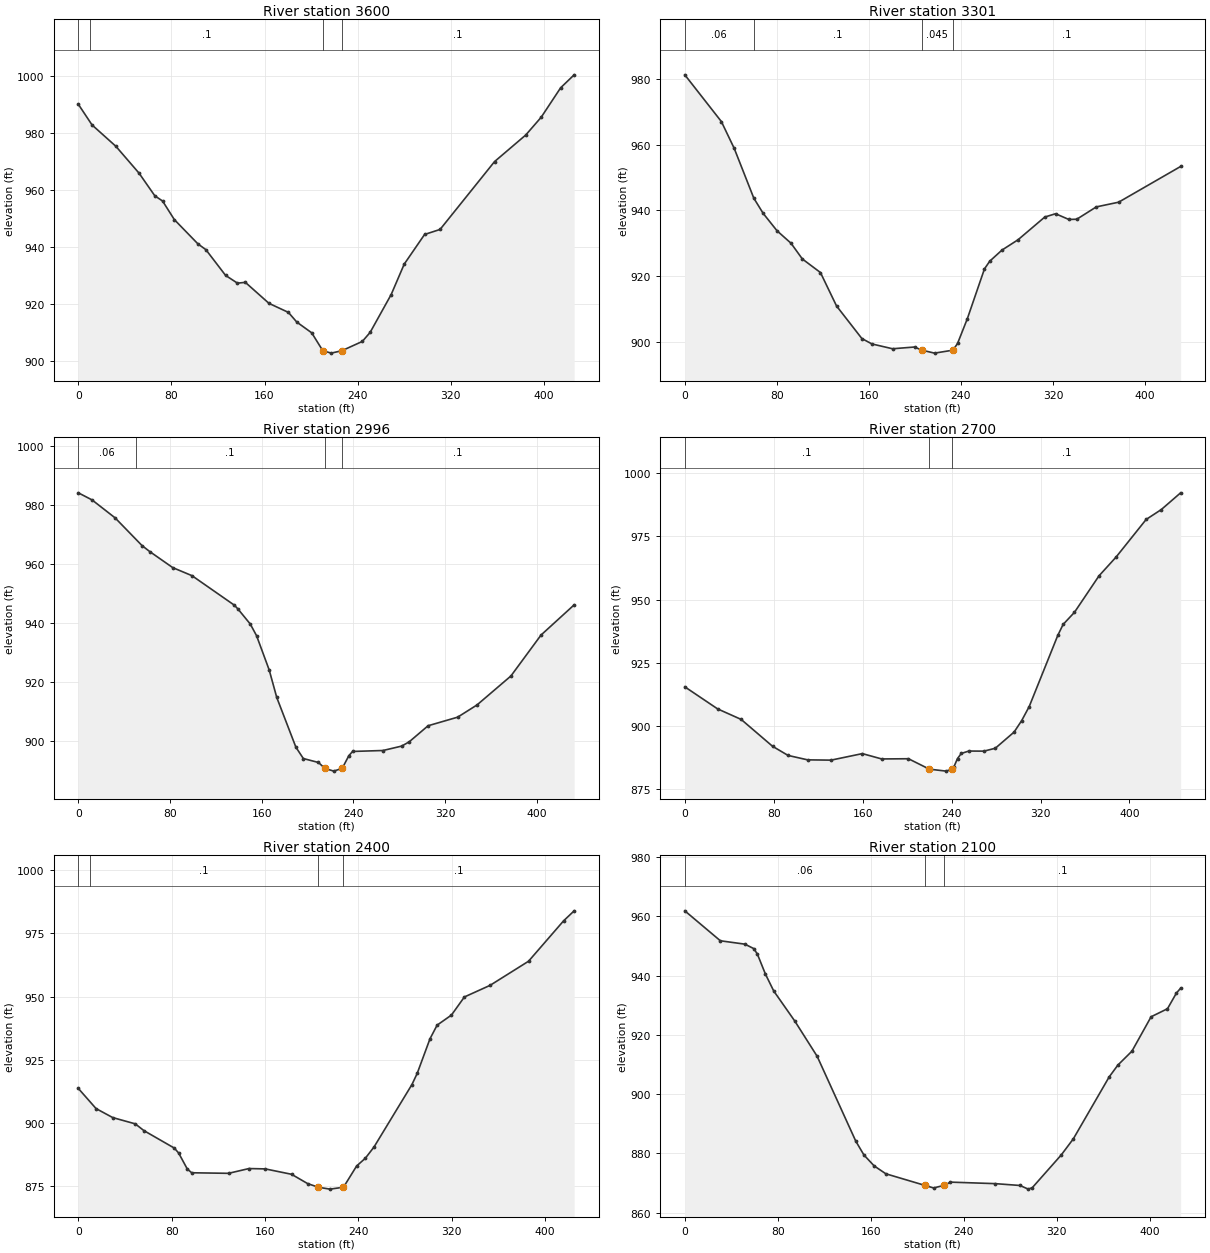
Type RM Length L Ch R = 1 ,3600    ,290.6,299,312.4
XS GIS Cut Line= 6
1681683.59253734537370.922602922 1681597.5720401537390.669938758
1681524.76247442537409.4658329191681426.60059726537428.552737013
1681352.97935343537442.8679970951681267.08812101537459.569079176
#Sta/Elev= 30
       0  990.07    11.8   982.8    32.3  975.29    52.2  965.85    65.7  957.92
    72.4  956.07    82.5  949.54   102.8     941   109.6  938.98   126.5  929.95
   136.7  927.22   143.5   927.5   163.8  920.12   180.5  916.94   187.7  913.54
   200.5  909.77  210.04903.4878   217.3  902.63  226.46903.4844     244  906.74
   250.7  909.91   268.8  923.23     280  933.91   297.5  944.33   310.8  946.09
   357.6  969.93   384.4  979.27   397.7  985.53   414.4  995.87     426 1000.42
#Mann= 4 ,-1,0
       0     .06       0      10      .1       0  210.04    .045       0
  226.46      .1       0
Bank Sta=210.04,226.46
XS Rating Curve= 0 ,0
Exp/Cntr(USF)=0,0
Exp/Cntr=0.3,0.1

Type RM Length L Ch R = 1 ,3301    ,311.3,304.8,290.2
XS GIS Cut Line= 6
1681694.68569101537297.6816076791681619.75834742537244.187948257
1681569.69775201 537187.977758841681498.48660834537117.742335007
1681444.04052301537066.1610733421681373.02032384537013.118200421
#Sta/Elev= 30
       0  981.23    31.8     967      43   958.8      60  943.67    68.1  939.06
    80.2  933.74    92.3  929.97   102.2  925.16   117.9  921.04   131.9  910.86
   153.9  900.95   162.6   899.3   180.6  897.83   199.7  898.36     206897.4052
   217.1   896.5  233.16897.4042   237.1  899.45   245.6  906.98   260.5  922.16
   265.1   924.5   275.7  927.87   289.7  931.02   312.9  937.93   322.3  938.94
   333.8   937.2   340.7  937.26   357.7  941.02   377.1  942.45     431  953.33
#Mann= 4 ,-1,0
       0     .06       0      60      .1       0     206    .045       0
  233.16      .1       0
Bank Sta=206,233.16
XS Rating Curve= 0 ,0
Exp/Cntr(USF)=0,0
Exp/Cntr=0.3,0.1

Type RM Length L Ch R = 1 ,2996    ,291.3,296.2,298.6
XS GIS Cut Line= 6
1681815.00631651   536866.7940181681725.60885751536885.864189833
1681649.41708076536903.5629733351681549.55146684536916.500611499
1681474.65529117536920.4431889211681387.27620085536925.042917252
#Sta/Elev= 30
       0  984.18      12  981.77    32.1  975.69    55.6   966.3    62.3  964.28
    82.4  958.83    99.2   956.1   136.3  946.07   139.6  944.68   150.1   939.7
   155.6  935.73   166.6  924.14   173.2  914.82   189.9  897.97   196.4  894.12
   209.6  892.78  215.17890.7939   222.9  889.85  230.35890.7904   236.1  895.07
   239.4  896.52   265.9  896.84   282.3  898.34   288.9  899.81   305.3  905.23
   331.1  908.14     348  912.28   377.6   922.1   403.9  935.98   432.8  946.21
#Mann= 4 ,-1,0
       0     .06       0      50      .1       0  215.17    .045       0
  230.35      .1       0
Bank Sta=215.17,230.35
XS Rating Curve= 0 ,0
Exp/Cntr(USF)=0,0
Exp/Cntr=0.3,0.1

Type RM Length L Ch R = 1 ,2700    ,289.6,300,306.5
XS GIS Cut Line= 6
1681817.70348959536697.4800521731681723.54324484536660.676976174
1681646.50041993536631.3417330091681549.83000959536605.751889169
1681477.32720184536586.5599984231681392.74042876536564.169623256
#Sta/Elev= 30
       0  915.45    29.5  906.72    50.7  902.55    78.9  891.93    92.9   888.3
   110.5  886.55   131.6  886.44   159.7  889.02   177.1  886.91   201.2  886.99
  219.99882.8704   235.1  882.09  240.34882.8693   241.9  883.62   245.3  887.07
   248.7  889.08   255.5  890.04   269.1     890   279.3  891.14   296.2  897.54
     303  902.06   309.8  907.64   335.5  935.79   340.3  940.13   350.5  944.93
   372.6  959.37   387.9  966.77     415  981.68   428.6  985.58     446  992.21
#Mann= 3 ,-1,0
       0      .1       0  219.99    .045       0  240.34      .1       0
Bank Sta=219.99,240.34
XS Rating Curve= 0 ,0
Exp/Cntr(USF)=0,0
Exp/Cntr=0.3,0.1

Type RM Length L Ch R = 1 ,2400    ,299.2,300,301
XS GIS Cut Line= 6
 1681921.6835966536617.6481908411681880.31228825536540.546310917
1681844.85140118536474.4591727551681797.57065584536386.342551082
1681763.46376868536319.5287083391681724.53471267536241.116791666
#Sta/Elev= 30
       0  913.64    15.2  905.68    29.5  902.12    48.8  899.64    56.2  896.97
    82.3  890.05      86  888.11    93.4  881.79    97.2  880.29   128.8  880.07
   146.3  881.96   160.3  881.82   182.8  879.69   196.7  875.98  205.85 874.563
   215.7  873.82  227.33 874.564   238.6  882.97   246.1  886.05   253.5  890.48
     286  915.17   290.5  919.56   301.5  933.29   307.6  938.68   319.9  942.67
     331  949.83     353  954.42     386  963.96     416  979.92   425.1   983.9
#Mann= 4 ,-1,0
       0     .06       0      10      .1       0  205.85    .045       0
  227.33      .1       0
Bank Sta=205.85,227.33
XS Rating Curve= 0 ,0
Exp/Cntr(USF)=0,0
Exp/Cntr=0.3,0.1

Type RM Length L Ch R = 1 ,2100    ,304.2,300,293.4
XS GIS Cut Line= 6
1682163.49052767536488.3144600091682131.25863676536406.967181757
1682103.63106734536337.2412713321682066.79452685536244.273281425
1682038.13447918 536174.956162841681991.20183025536099.206970513
#Sta/Elev= 30
       0  961.84    30.6  951.74    51.7   950.6    59.3  949.11    62.4  947.29
    69.4  940.48    76.5  934.82    94.7  924.63   113.9  912.76   147.1  884.17
   154.1  879.51   162.9  875.82     173  873.15  206.42  869.26   214.1  868.38
  223.17  869.26   228.6  870.34   267.1  869.83   288.4  869.21   295.5  867.98
     299  868.48   323.9  879.51   334.3  884.95   365.1  905.81   372.6  909.81
   384.7   914.5   401.2  926.11   415.3  928.82     423  934.12   426.6  935.74
#Mann= 3 ,-1,0
       0     .06       0  206.42    .045       0  223.17      .1       0
Bank Sta=206.42,223.17
XS Rating Curve= 0 ,0
Exp/Cntr(USF)=0,0
Exp/Cntr=0.3,0.1