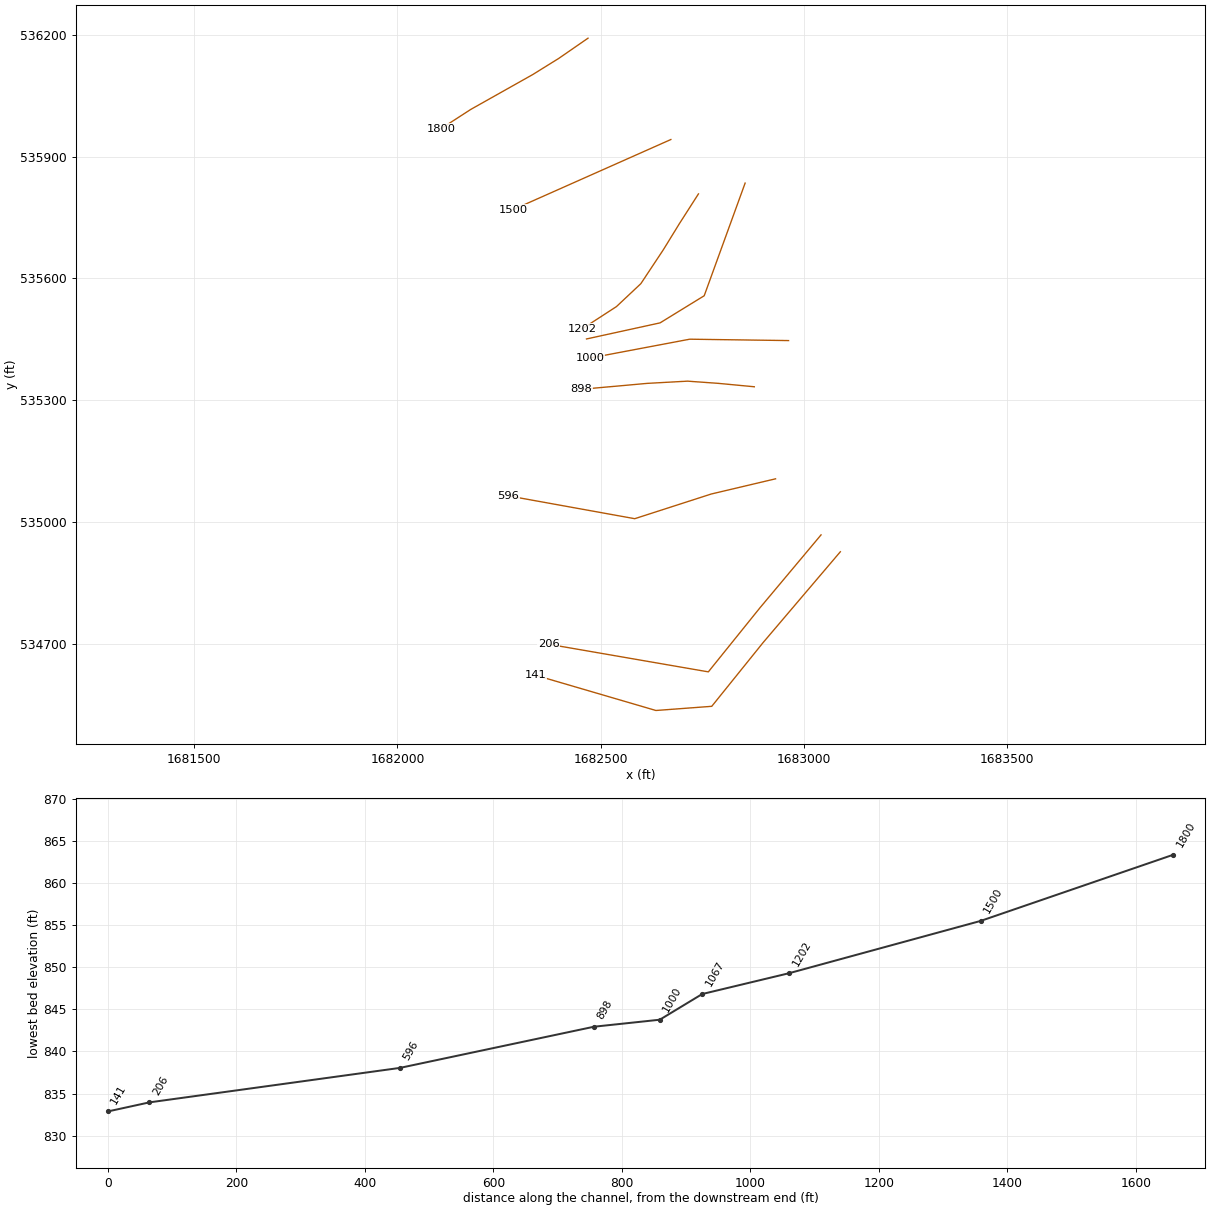
HEC-RAS study WhetstoneRn.prj: WhetstoneRn

--- WhetstoneRn.g01 (geometry) --- (continued)

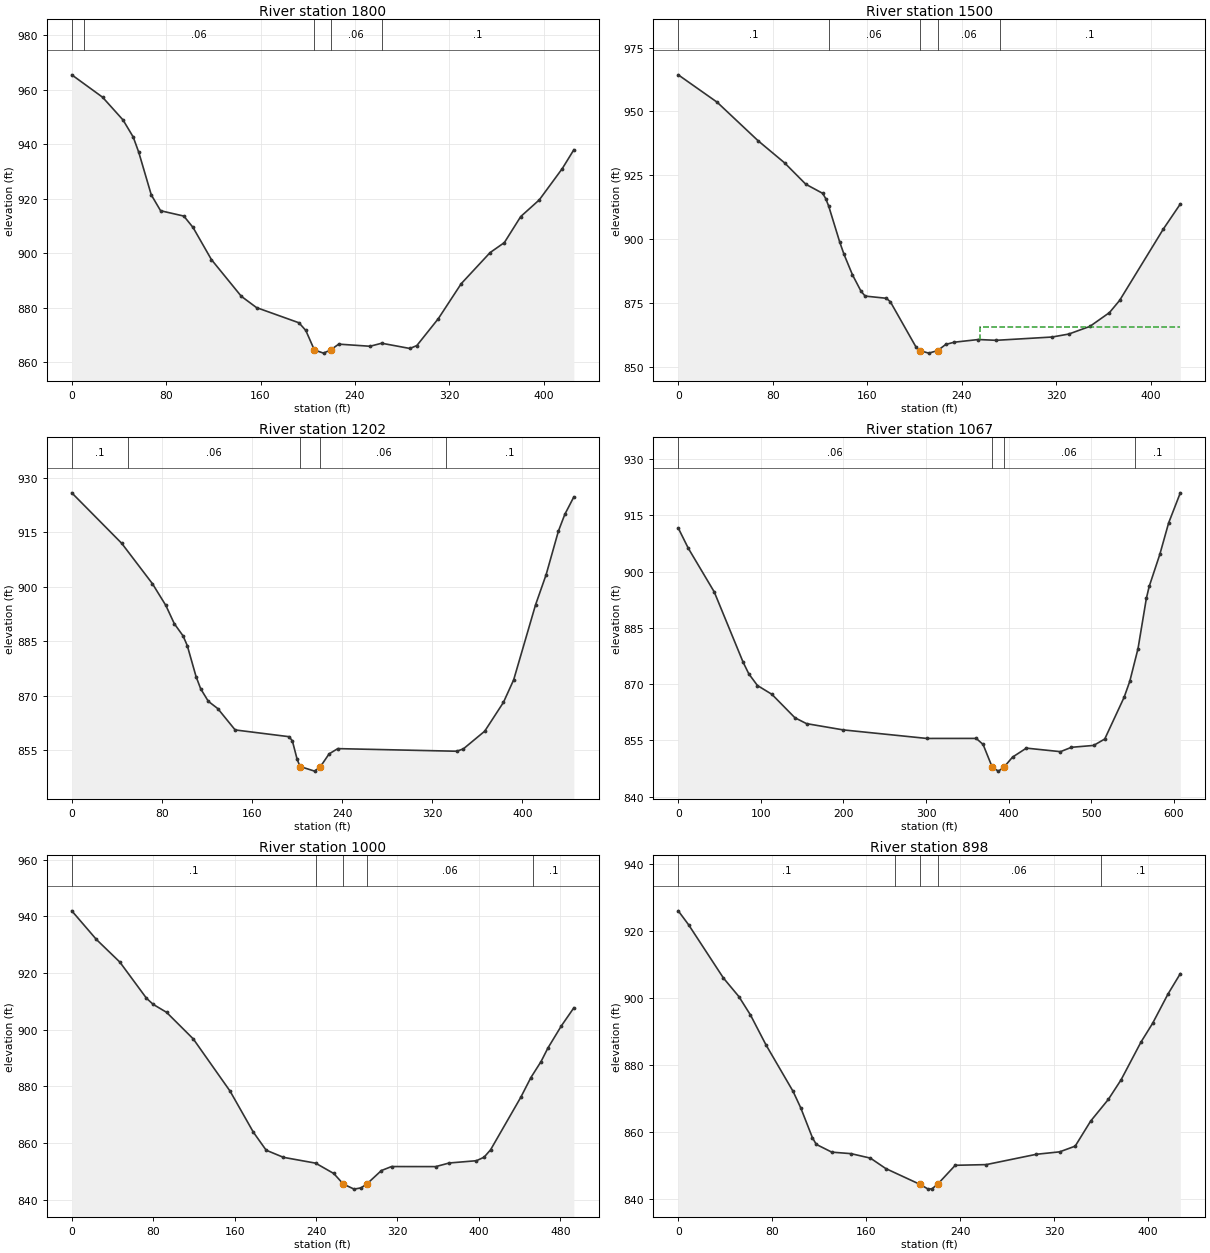
Type RM Length L Ch R = 1 ,1800    ,300.2,300,298.5
XS GIS Cut Line= 6
 1682468.9758091536191.4544894251682396.70167543536141.534641758
1682332.91735417536101.9494190961682245.75972009536052.923270419
1682180.39206867536016.1533308331682106.77115293535968.558281675
#Sta/Elev= 30
       0  965.47    26.1  957.26    43.5  948.88    52.1  942.64    56.8  937.03
    67.4  921.41    75.3   915.6      95  913.64   102.8  909.46   118.4  897.66
   143.7  884.21   156.6  880.06   192.6  874.48   198.4  871.66  205.64864.5093
   213.4  863.35  219.34864.5073   226.3  866.65   252.8  865.87   262.7  866.98
   286.6  865.06   292.5  866.12   310.7  875.99   330.1  888.82   354.6  900.24
   366.7  903.91   380.6  913.48   396.3  919.58   415.8  931.07   425.6  937.97
#Mann= 5 ,-1,0
       0      .1       0      10     .06       0  205.64    .045       0
  219.34     .06       0  262.91      .1       0
Bank Sta=205.64,219.34
XS Rating Curve= 0 ,0
Exp/Cntr(USF)=0,0
Exp/Cntr=0.3,0.1

Type RM Length L Ch R = 1 ,1500    ,292,298.3,302.1
XS GIS Cut Line= 6
1682672.95998117535942.0639120941682593.00147967535906.527237758
 1682524.4655275535876.0669968431682433.08414859535835.453561008
1682364.54885259535804.9920077621682284.56705718535769.507170588
#Sta/Elev= 30
       0  964.33    32.9  953.63    67.7  938.51      90  929.91     108  921.54
   122.3  917.97   124.9  915.87   127.4  912.93   136.7  898.93   140.3  894.16
   147.5   886.1   154.7  879.73   158.2   877.8   176.2  876.94   179.6  875.54
   201.3  857.85  204.36856.4772   212.1  855.49  219.61856.4778   226.4  858.88
   233.6  859.76   254.1  860.81   269.1   860.5   316.5  861.79   330.6  862.95
   348.5  865.96     365  871.33   373.6  876.09   410.7  904.07     425  913.81
#Mann= 5 ,-1,0
       0      .1       0   127.5     .06       0  204.36    .045       0
  219.61     .06       0   272.5      .1       0
#XS Ineff= 2 , 0
                           255.6          865.61
Permanent Ineff=
       F       F
Bank Sta=204.36,219.61
XS Rating Curve= 0 ,0
Exp/Cntr(USF)=0,0
Exp/Cntr=0.3,0.1

Type RM Length L Ch R = 1 ,1202    ,139.7,135.1,131.2
XS GIS Cut Line= 6
1682740.84764068 535808.221003921682693.64497918535734.528237924
1682654.33698693535670.6543499231682599.04247808535587.263768673
1682539.01471101535530.8449182511682454.53686158535476.053361177
#Sta/Elev= 30
       0  925.83    44.3  911.95    71.6  900.83    83.5  894.85      91  889.84
    98.8  886.47   102.5  883.82   110.3   875.3   114.4  871.94   121.2  868.48
   129.6  866.48     145  860.61   192.9  858.75   195.8  857.58     200  852.55
  202.59850.5513   215.5  849.28  220.75850.5508   228.4  854.03   236.1  855.47
   341.6  854.75   347.5  855.39   366.5  860.27   383.1  868.19   392.2   874.4
   411.6  895.01     421  903.32   431.9   915.3   437.6  919.92   445.6  924.71
#Mann= 5 ,-1,0
       0      .1       0      50     .06       0  202.59    .045       0
  220.75     .06       0  332.57      .1       0
Bank Sta=202.59,220.75
XS Rating Curve= 0 ,0
Exp/Cntr(USF)=0,0
Exp/Cntr=0.3,0.1

Type RM Length L Ch R = 1 ,1067    ,68.3,66.1,63.8
XS GIS Cut Line= 4
1682855.72959291535834.8203520341682755.00635197535557.548508999
1682646.36105838535490.7769223091682465.28556905535451.166659019
#Sta/Elev= 30
       0   911.6    12.2   906.2    43.6  894.57    78.5  875.87    85.5  872.72
    95.9  869.63   113.4  867.28   141.3  861.03   155.3  859.47   199.7   857.8
   301.1  855.52   360.8  855.53   369.1  853.92  380.27847.8063   387.7  846.81
   394.1847.8052   404.8  850.55   421.5  852.94   462.8     852   476.1  853.16
     503  853.66   516.4  855.37   539.9  866.51   546.7  870.74   556.7  879.47
   566.8  892.85   570.2  896.02   583.1  904.58   593.7  912.92   607.9  920.98
#Mann= 4 ,-1,0
       0     .06       0  380.27    .045       0   394.1     .06       0
  552.52      .1       0
Bank Sta=380.27,394.1
XS Rating Curve= 0 ,0
Exp/Cntr(USF)=0,0
Exp/Cntr=0.3,0.1

Type RM Length L Ch R = 1 ,1000    ,104.6,102.3,99.4
XS GIS Cut Line= 3
 1682962.6773038 535447.205632691682719.35711501535450.600798115
1682473.77348261535404.200203974
#Sta/Elev= 30
       0     942    24.2  931.89    47.2  923.92    73.4  911.14      80  908.98
    93.1  906.18   119.4  896.78   155.5  878.37   178.4  863.87     191   857.5
     208  854.98   239.6  852.93   257.4  849.28  266.82845.5435   277.4  843.76
   284.1   844.2  289.85 845.545   304.2  850.32   314.2  851.73   357.6  851.71
   370.9  852.99   397.6  853.79   405.1  855.03   411.5  857.65   441.1  876.14
   451.1  883.15   461.1  888.81   467.8  893.56   481.1  901.43   493.3  907.76
#Mann= 5 ,-1,0
       0      .1       0     240     .06       0  266.82    .045       0
  289.85     .06       0  453.34      .1       0
Bank Sta=266.82,289.85
XS Rating Curve= 0 ,0
Exp/Cntr(USF)=0,0
Exp/Cntr=0.3,0.1

Type RM Length L Ch R = 1 ,898     ,299.1,302.2,303.5
XS GIS Cut Line= 6
1682878.33949168535333.4998405131682789.89314626535341.897461504
1682714.05307484535347.3196947571682614.13857651535341.839390755
1682539.44646868535335.0500342551682452.29014692535327.302674428
#Sta/Elev= 30
       0  926.07     8.8  921.92    38.5  905.98    51.7  900.42    61.5  894.95
    74.7  886.02    97.8  872.11   104.3   867.2   114.2  858.32   117.5   856.3
   130.7  853.98   147.1  853.53   163.6  852.19   176.7  849.07  205.64844.3738
   212.8  842.93   216.1  843.05  220.75844.3732   235.8  850.05   262.1  850.25
   304.9  853.34   324.7  854.07   337.9  855.77   351.1  863.27   366.1  869.72
   376.9  875.54   393.9  886.85   403.8  892.45   416.9  901.21   427.4   907.3
#Mann= 5 ,-1,0
       0      .1       0  184.88     .06       0  205.64    .045       0
  220.75     .06       0  359.94      .1       0
Bank Sta=205.64,220.75
XS Rating Curve= 0 ,0
Exp/Cntr(USF)=0,0
Exp/Cntr=0.3,0.1

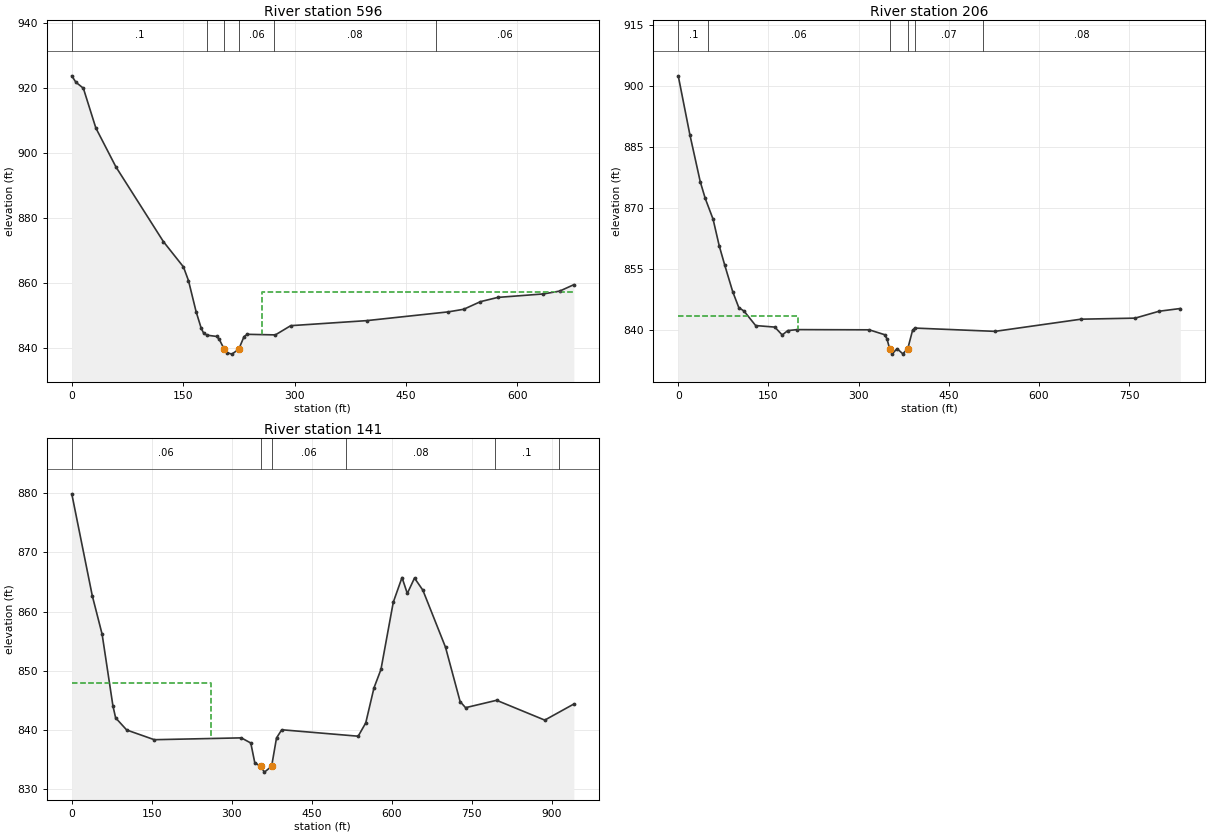
Type RM Length L Ch R = 1 ,596     ,371.4,389.8,390.8
XS GIS Cut Line= 5
1682930.66222167535106.9451754991682845.50491168535086.833011001
1682772.51325975535069.593872249 1682584.0405113535008.810107902
1682273.35714076535064.928577444
#Sta/Elev= 30
       0  923.71     5.5  921.75    15.6  919.89    32.4  907.67    59.4   895.7
   123.4  872.68   150.4  864.89   157.2  860.67   167.4  851.16   174.3  846.03
   177.7  844.44   182.5  843.86     195  843.49   198.4  842.71  205.37839.5188
   208.7  838.51   215.6  838.04  224.81839.5214     232  843.43   236.3  844.14
   274.2  843.96   294.9   846.8   397.1  848.35   507.1  851.05   527.9  851.85
   550.4  854.19   573.8   855.5   635.2  856.57   657.1  857.44   676.2  859.42
#Mann= 6 ,-1,0
       0      .1       0   182.5     .06       0  205.37    .045       0
  224.81     .06       0   272.5     .08       0  490.53     .06       0
#XS Ineff= 2 , 0
                          255.62          857.16
Permanent Ineff=
       F       F
Bank Sta=205.37,224.81
XS Rating Curve= 0 ,0
Exp/Cntr(USF)=0,0
Exp/Cntr=0.3,0.1

Type RM Length L Ch R = 1 ,206     ,60.6,64.8,61.6
XS GIS Cut Line= 4
 1683042.5984162534968.9180324791682891.94469078534789.109401161
1682765.19184825534631.8000698071682372.26740684534699.800184509
#Sta/Elev= 30
       0  902.53    19.3  888.07    36.6  876.46    44.9  872.33      58  867.19
    68.2  860.64    77.5  855.82    90.6  849.36   100.8  845.41   109.4  844.57
   128.8  840.99   160.7  840.61     173  838.67   182.3  839.75   197.9  839.99
   317.8  839.94   343.2  838.75   347.3  837.73  351.71835.2931   355.7  833.95
   364.1   835.3   373.6  834.03  381.92835.2935   389.9  839.81   393.6  840.37
   527.1  839.56   670.1  842.56   760.2  842.82   800.1  844.52   835.4  845.19
#Mann= 6 ,-1,0
       0      .1       0      50     .06       0  351.71    .045       0
  381.92     .06       0  394.58     .07       0   506.6     .08       0
#XS Ineff= 2 , 0
          198.56   843.3
Permanent Ineff=
       F       F
Bank Sta=351.71,381.92
XS Rating Curve= 0 ,0
Exp/Cntr(USF)=0,0
Exp/Cntr=0.3,0.1

Type RM Length L Ch R = 1 ,141     ,,,
XS GIS Cut Line= 5
1683090.12994103534927.4332467791682900.35496792534704.311805513
1682773.60212539534547.0024741591682636.20350585534536.721466035
1682340.15924887534623.385713367
#Sta/Elev= 30
       0   879.9    38.4   862.7    56.9  856.17    77.1  844.09    82.2  842.04
     103  839.99   154.7  838.35   317.8  838.66   335.6  837.79   343.1  834.45
  353.94833.8547   361.2  832.87  374.63833.8552   383.8  838.64   393.6  840.03
   536.9  838.94   551.1  841.19   566.5   847.1   579.6  850.22   602.7  861.58
   619.1  865.76     629  863.06   642.5  865.67   658.2  863.61   700.6  853.98
     728   844.8   738.2  843.76   796.4  845.01   886.7  841.66   941.2  844.38
#Mann= 6 ,-1,0
       0     .06       0  353.94    .045       0  374.63     .06       0
  514.93     .08       0  792.72      .1       0  912.72     .08       0
#XS Ineff= 2 , 0
          261.16  847.96
Permanent Ineff=
       F       F
#Block Obstruct= 2 , 0
           75.18  837.55
Bank Sta=353.94,374.63
XS Rating Curve= 0 ,0
Exp/Cntr(USF)=0,0
Exp/Cntr=0.3,0.1
LCMann Table=0

Chan Stop Cuts=-1
Use User Specified Reach Order=0
Composite Channel Slope=5